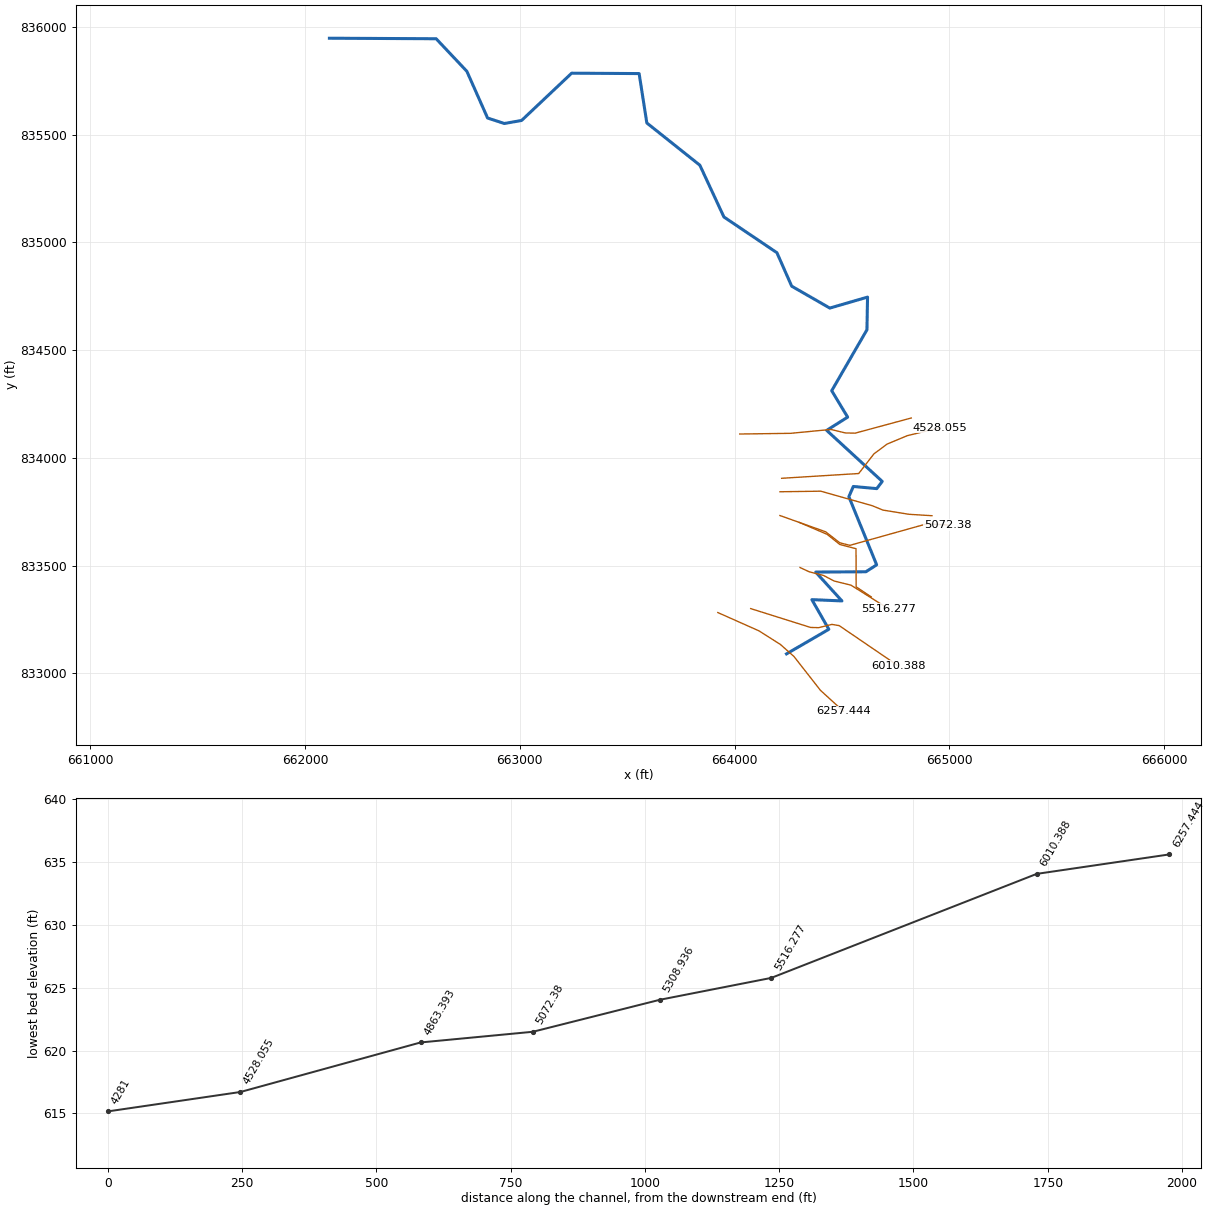
--- 13681_ras.prj (project) ---

Proj Title=13681
Current Plan=p01
Default Exp/Contr=0.3,0.1
English Units
Geom File=g01
Flow File=f01
Plan File=p01
Y Axis Title=Elevation
X Axis Title(PF)=Main Channel Distance
X Axis Title(XS)=Station
BEGIN DESCRIPTION:
RFD model 13681 exported to HEC-RAS
END DESCRIPTION:

--- 13681_ras.p01 (plan) ---

Plan Title=Plan 01
Program Version=4.10
Short Identifier=Plan 01
Geom File=g01
Flow File=f01
Subcritical Flow
Calc Critical at every XS
Secant Critical Depth

--- 13681_ras.f01 (steady flow) ---

Flow Title=Flow 01
Program Version=5.01
Number of Profiles= 6
Profile Names=10yr,25yr,50yr,100yr,100plus,500yr
River Rch & RM=13681,8,6257.444
   429.4  692.18  939.73 1166.63 1703.28 2608.38
River Rch & RM=13681,8,6010.388
   432.6   697.4  946.87 1175.54 1716.29  2625.7
River Rch & RM=13681,8,5516.277
  436.07  703.07  954.64 1185.27 1730.49  2644.7
River Rch & RM=13681,8,5308.936
  466.39  752.65 1022.67 1270.38 1854.75 2809.99
Boundary for River Rch & Prof#=13681,8,1
Up Type= 0
Dn Type= 2
Boundary for River Rch & Prof#=13681,8,2
Up Type= 0
Dn Type= 2
Boundary for River Rch & Prof#=13681,8,2
Up Type= 0
Dn Type= 2
Boundary for River Rch & Prof#=13681,8,2
Up Type= 0
Dn Type= 2
Boundary for River Rch & Prof#=13681,8,2
Up Type= 0
Dn Type= 2
Boundary for River Rch & Prof#=13681,8,2
Up Type= 0
Dn Type= 2

--- 13681_ras.g01 (geometry) ---

Geom Title=13681
Program Version=4.10

River Reach=13681,8
Reach XY= 30
664242.097048858833089.900346828664439.107784177833204.001023877
664360.238966433833341.732867889664500.117270078833335.813221672
664377.905672831833469.748579535664611.610535671833471.069838285
  664661.8002878833503.240413086664532.344472856833819.713115013
664553.275647723833867.050026982664662.337890208833857.104106109
664687.824258832833890.487526982 664429.14370325834127.466693668
664526.795411919834188.898898307 664452.58120328834311.494471422
664616.621857371 834594.40312566664619.383544891834746.053247827
664443.744006811834695.142874119664266.316792906834796.676548869
664197.388276663834952.181894242663950.669818816835118.022237639
663838.597506043835358.405713372663591.709765763835554.440396522
663555.879814392835783.716693656663241.643703279835785.452804761
663008.636855782835566.000442782662928.275647702835551.945860312
662850.207226393835577.443432224662753.796481067835794.133360332
662610.765788464835945.418007457662113.801554396835947.777677568

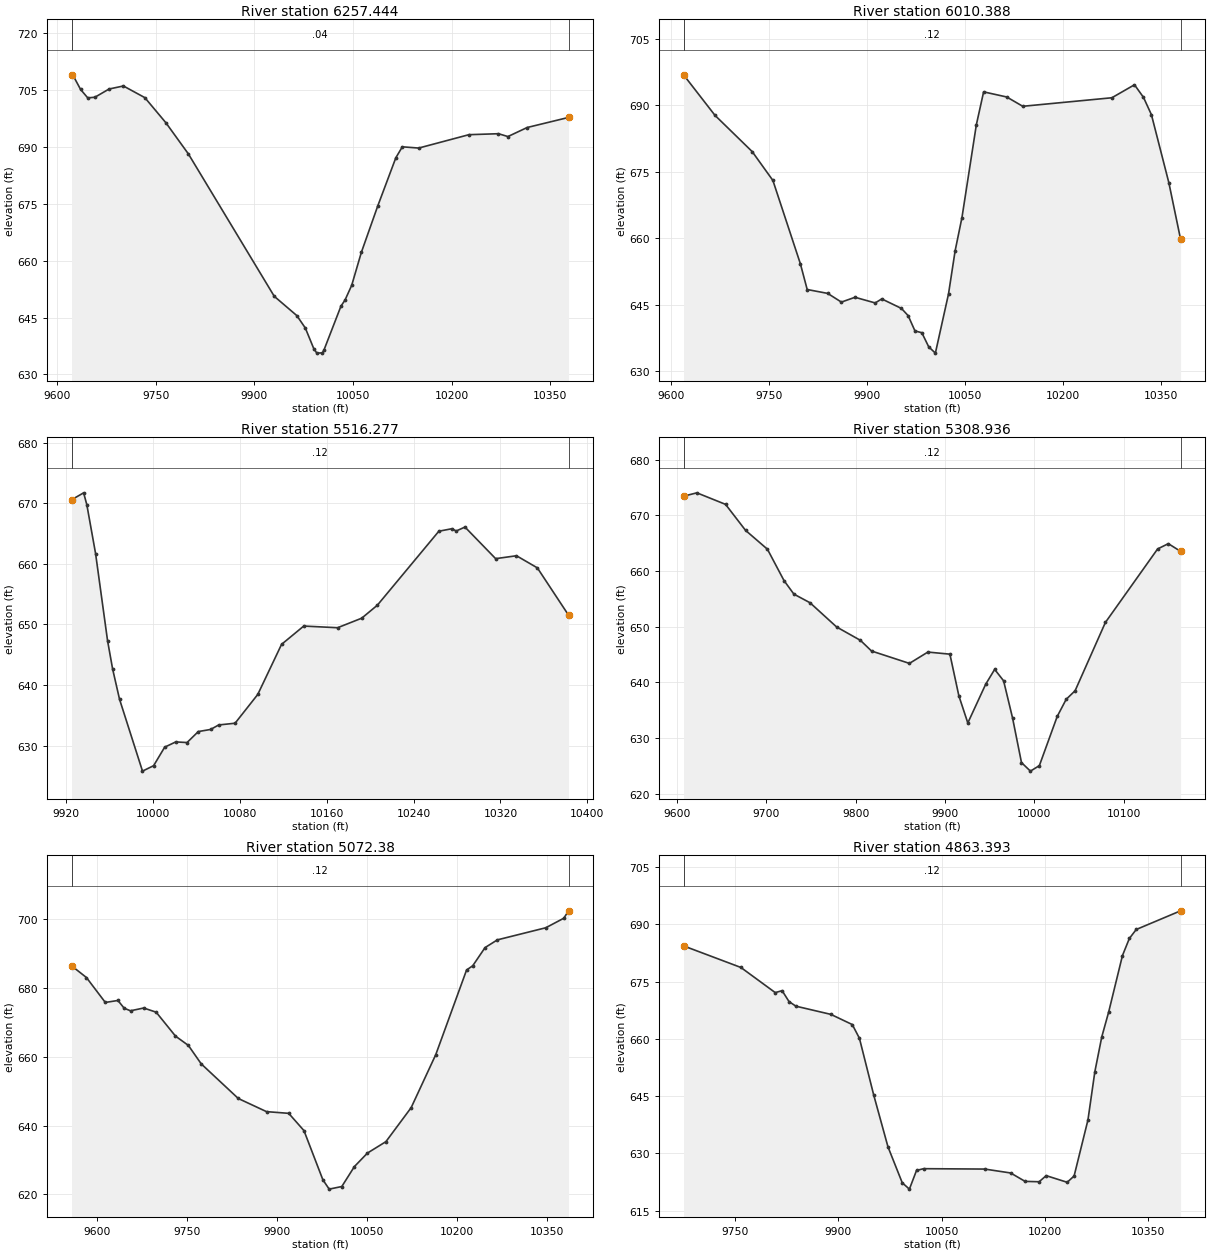
Type RM Length L Ch R = 1 ,6257.444,247.055500,247.055500,247.055500
XS GIS Cut Line= 6
663922.305603948833281.769255309664114.011754445833196.783621128
 664213.60093075833133.670521096664276.842758558833077.765578898
664399.948250469832921.023528264664506.299714959832824.227315371
#Sta/Elev= 30
9622.166709.00929625.091708.65999635.946705.15819646.802702.93969657.657703.0955
9679.368705.27559701.079706.06549733.646702.99389765.681696.36259799.839688.1522
9930.427650.59889964.708645.51539977.643642.23779990.577 636.761 9995.17635.6172
10003.59635.690810005.98636.432310031.85648.021710037.92649.585710048.15653.4983
10062.83662.193510087.74 674.41910115.24687.135110125.11690.024910150.02689.6964
10226.36693.223810271.28693.479610285.64 692.73110314.92695.116110377.79697.7709
#Mann= 3 , 0 , 0
9622.166    0.04       09622.166    0.04       010377.79    0.04       0
#XS Ineff= 2 , 0
       0                               0
Bank Sta=9622.166,10377.79
Exp/Cntr=0.3,0.1

Type RM Length L Ch R = 1 ,6010.388,494.110900,494.110900,494.110900
XS GIS Cut Line= 6
664075.317507418833300.173815761664354.229293464 833212.64341599
664391.885279272833211.644539874664453.254600427833226.799696247
 664487.52117776833221.090565949664761.593023516833034.746703133
#Sta/Elev= 30
9619.772 696.8999667.799687.76079724.836679.55759756.456673.05089798.474654.2547
9808.934648.42989840.313647.55259861.233645.58959882.073646.67559912.962645.3997
9923.011646.30699953.178644.15489963.425642.52059973.812639.08249984.339638.6741
9994.866635.485810005.06634.067510025.14647.423810035.35657.231910045.71664.6644
10067.75685.633110078.87693.053310114.25691.895510138.75689.794910275.09691.7214
10309.67694.653310323.44691.819610335.62687.890910362.23672.566410380.19659.7943
#Mann= 3 , 0 , 0
9619.772    0.12       09619.772    0.12       010380.19    0.12       0
#XS Ineff= 2 , 0
       0                               0
Bank Sta=9619.772,10380.19
Exp/Cntr=0.3,0.1

Type RM Length L Ch R = 1 ,5516.277,207.341500,207.341500,207.341500
XS GIS Cut Line= 6
664304.876502534833490.934075573664347.808215373833471.012681864
664414.891753862833453.734330587664463.555229248833428.336859119
664542.240857225833408.869625919664715.946077745833300.060968138
#Sta/Elev= 30
9924.802670.55319935.962671.7026  9938.9669.74519946.986661.6718 9958.01647.3018
9962.657642.65069969.034637.64859990.194625.789110000.44626.687410010.63629.7423
10020.83 630.60910031.22630.504610041.63632.318110052.91632.662610060.39633.4069
10075.47633.6911 10096.4 638.44410118.32646.705410138.75649.722910169.93649.4473
10192.13651.019610206.54653.1591 10263.2665.367610275.23665.781110279.23665.4048
10287.27666.055810315.52660.843310334.74661.321710353.96659.322710382.67651.5278
#Mann= 3 , 0 , 0
9924.802    0.12       09924.802    0.12       010382.67    0.12       0
#XS Ineff= 2 , 0
       0                               0
Bank Sta=9924.802,10382.67
Exp/Cntr=0.3,0.1

Type RM Length L Ch R = 1 ,5308.936,236.555900,236.555900,236.555900
XS GIS Cut Line= 6
664301.261341751833700.467523113664431.305549681833644.710520312
664490.257981509833597.728213623664565.778814852833578.196963608
664566.314607054833401.090950429664636.428842187833354.554953665
#Sta/Elev= 30
 9607.27 673.4569622.169674.06649654.289671.99269676.669 667.3239701.185663.9311
9719.762658.29059730.814655.86189748.835654.31459778.671649.95539805.296647.5552
9817.741645.63629860.169643.41189880.827645.44759905.495645.07029915.522637.5871
9925.549632.70589945.602639.67659955.629642.33499965.636640.27659975.642633.6068
9985.648625.58169995.655624.049210005.66625.035210025.67633.882510035.68636.9523
10045.69638.497710079.62650.775410138.05663.976710150.05664.931110163.77663.5523
#Mann= 3 , 0 , 0
 9607.27    0.12       0 9607.27    0.12       010163.77    0.12       0
#XS Ineff= 2 , 0
       0                               0
Bank Sta=9607.27,10163.77
Exp/Cntr=0.3,0.1

Type RM Length L Ch R = 1 , 5072.38,208.987100,208.987100,208.987100
XS GIS Cut Line= 6
664211.343645661833732.158611806664423.979514672833656.883187919
664490.257981509833605.540713623664537.132981509833593.821963608
664895.139440841833693.599387332664992.830167694833688.133583653
#Sta/Elev= 30
9558.021686.4816 9582.84683.07179614.314 675.8139635.297676.39059645.789674.1242
 9656.28 673.3889678.202674.19769698.995  672.989731.169666.02149752.618663.3115
9774.067657.9366 9835.76647.87069882.731644.04729919.715643.55359945.114638.5279
9976.615624.21349987.116621.501310008.12622.259610029.12628.062110050.86631.9953
10081.62635.319210123.62645.202610164.67660.656110215.93685.257510226.19686.4915
10246.69691.7757 10267.2694.024410347.81697.542710377.85700.322510385.69702.4716
#Mann= 3 , 0 , 0
9558.021    0.12       09558.021    0.12       010385.69    0.12       0
#XS Ineff= 2 , 0
       0                               0
Bank Sta=9558.021,10385.69
Exp/Cntr=0.3,0.1

Type RM Length L Ch R = 1 ,4863.393,335.337300,335.337300,335.337300
XS GIS Cut Line= 6
664211.612148196833842.519880295664401.716314852833845.124046952
664640.540119499833778.038708553664690.641228884 833757.55070743
664811.550285459833737.954078048 664919.38269496833731.333146557
#Sta/Elev= 30
9674.694684.3456 9758.09678.69479808.095672.10689818.096672.61389828.096669.7681
9838.097668.55699889.001666.40839920.162663.74329930.549 660.1639951.323645.3109
9972.097631.72429992.871622.312610003.26620.651310013.65625.543610024.03626.0054
10112.88625.904110150.61624.879710171.59 622.67910192.06622.5836 10202.3624.1825
10232.84622.4421 10242.9624.079610263.04638.7536 10273.1651.409210283.17660.5135
10293.22667.040910313.26681.810910323.28686.2771 10333.3688.6324 10397.8693.5215
#Mann= 3 , 0 , 0
9674.694    0.12       09674.694    0.12       0 10397.8    0.12       0
#XS Ineff= 2 , 0
       0                               0
Bank Sta=9674.694,10397.8
Exp/Cntr=0.3,0.1

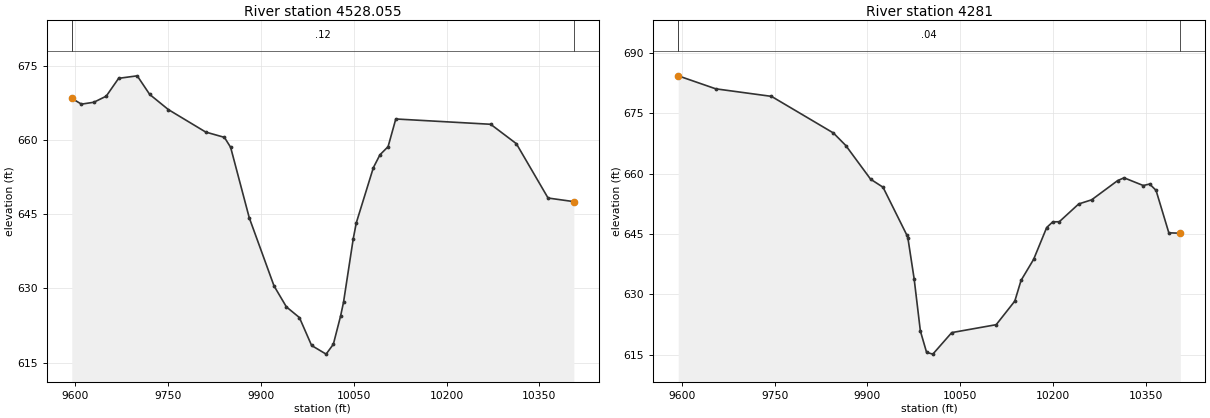
Type RM Length L Ch R = 1 ,4528.055,247.055400,247.055400,247.055400
XS GIS Cut Line= 6
664219.340353775 833905.00261752664578.306186885833927.168700913
664649.188121341834018.413783739664710.473637189834063.820400731
 664804.60960722834102.902378118664955.760143819834139.316798528
#Sta/Elev= 30
9594.416 668.4919610.078 667.324 9630.08667.70559650.082668.93689670.111672.5479
9700.196673.05629720.315669.29249750.494666.22159810.851661.6716 9841.03660.5986
9851.089658.5893 9881.22644.30799921.222630.52079941.222626.27489962.238624.1136
9981.954618.459710005.38  616.7110017.07618.714410028.75624.409110033.52627.2181
10049.27640.105910054.23643.324410081.75654.472510092.38  657.0710105.53 658.717
10117.97664.320210271.28663.246710312.78659.3196   10364648.316210405.67647.5849
#Mann= 3 , 0 , 0
9594.416    0.12       09594.416    0.12       010405.67    0.12       0
#XS Ineff= 2 , 0
       0                               0
Bank Sta=9594.416,10405.67
Exp/Cntr=0.3,0.1

Type RM Length L Ch R = 1 ,    4281,0.000000,0.000000,0.000000
XS GIS Cut Line= 6
664024.310632435834110.553393353664261.342947215834113.736283218
664448.901860374834131.761058515664515.936726844834115.494227588
664561.581147171834114.544122735664822.953565423834184.912736361
#Sta/Elev= 30
9594.181684.2773 9654.87 681.0489744.878679.17599844.959670.08519865.017666.9697
9905.133 658.6049925.191656.61069963.849644.67219965.422643.96739975.481633.8764
 9985.54620.91429995.599615.595310005.72615.163210036.25620.507910108.12 622.475
10138.19628.337210148.28633.471210168.66638.717410189.74646.609110199.61648.0188
10210.07 648.03810241.47652.4573 10262.4653.486310304.27658.242910314.73658.9538
10345.83657.036210356.16657.406510366.49655.830310387.15645.2887 10405.7645.1931
#Mann= 3 , 0 , 0
9594.181    0.04       09594.181    0.04       0 10405.7    0.04       0
#XS Ineff= 2 , 0
       0                               0
Bank Sta=9594.181,10405.7
Exp/Cntr=0.3,0.1